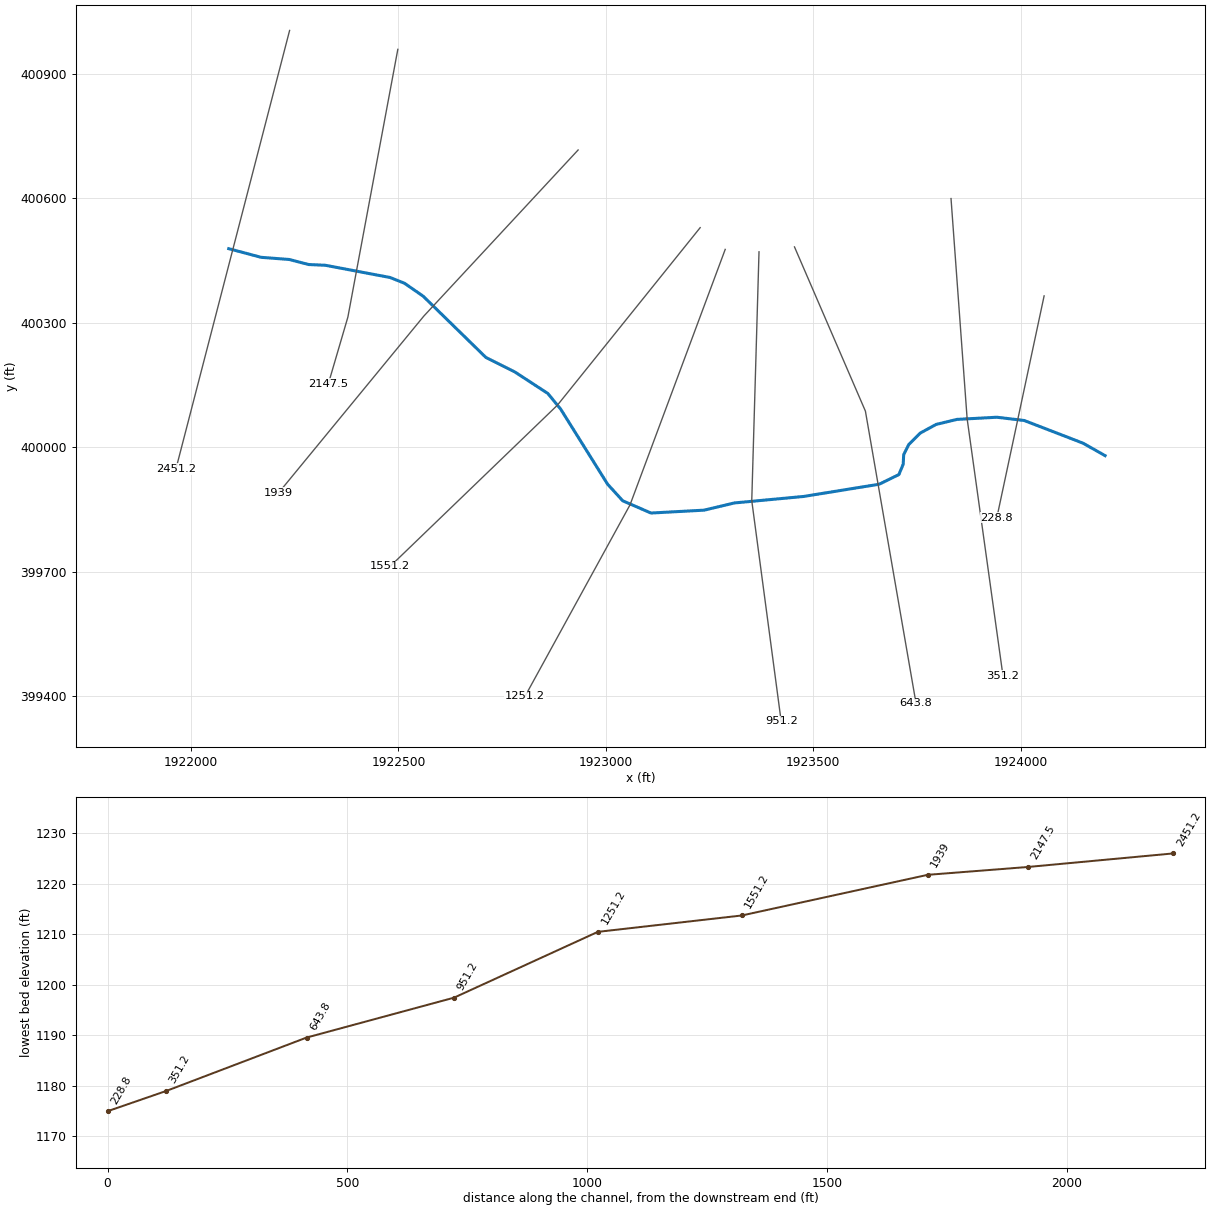
--- JenkinsBrh.prj (project) ---

Proj Title=JenkinsBrh
Current Plan=p01
Default Exp/Contr=0,0
English Units
Geom File=g01
Flow File=f01
Plan File=p01
BEGIN DESCRIPTION:
END DESCRIPTION:
DSS Export Rating Curves= 0
DSS Export Rating Curve Sorted= 0
DSS Export Volume Flow Curves= 0
DXF OffsetX= 0
DXF OffsetY= 0
DXF ScaleX= 0
DXF ScaleY= 0

--- JenkinsBrh.p01 (plan) ---

Plan Title=Floodplain
Program Version=4.00
Geom File=g01
Flow File=f01
K Sum by GR=0
Std Step Tol=0.01
Critical Tol=0.01
Num of Std Step Trials=20
Max Error Tol=0.3
Flow Tol Ratio=0.001
Split Flow NTrial=30
Split Flow Tol=0.02
Split Flow Ratio=0.02
Log Output Level=0
Friction Slope Method=1
Unsteady Friction Slope Method=2
Unsteady Bridges Friction Slope Method=1
Global Log Level=0
CheckData=False
Run HTab=0
Run UNet=0
Run PostProcess=0
UNET Theta=0
UNET Theta Warmup=0
UNET ZTol=0
UNET ZSATol=0
UNET MxIter=0
UNET MaxInSteps=0
UNET DtIC=0
UNET DtMin=0
UNET MaxCRTS=0
UNET WFStab=0
UNET SFStab=0
UNET WFX=0
UNET SFX=0
UNET DSS MLevel=0
UNET DZMax Abort=0
UNET Convert EG Bridges=0
UNET Use Existing IB Tables=0
UNET Froude Limit=0
UNET Froude Power=0
Write IC File=0
Echo Input=False
Echo Output=False
Write Detailed=0

--- JenkinsBrh.f01 (steady flow) ---

Flow Title=NFF Regression Equation
Program Version=4.00
Number of Profiles=1
Profile Names=P100yr
River Rch & RM=JenkinsBrh,Main      ,2451.2
663.0893
River Rch & RM=JenkinsBrh,Main      ,228.8
721.9677
Boundary for River Rch & Prof#=JenkinsBrh,Main      ,1
Up Type=0
Dn Type=3
Dn Slope=0.031505

--- JenkinsBrh.g01 (geometry) ---

Geom Title=USGS 3m DEM
Program Version=4.00

River Reach=JenkinsBrh     ,Main
Reach XY= 30
     1922091.050      400478.756     1922169.175      400457.923
     1922236.883      400452.715     1922283.758      400440.562
     1922323.689      400438.826     1922479.939      400409.312
     1922514.661      400395.423     1922559.800      400364.173
     1922710.842      400216.604     1922780.286      400181.881
     1922860.147      400129.798     1922891.397      400091.603
     1923004.244      399911.048     1923040.703      399871.117
     1923108.797      399841.604     1923236.883      399848.548
     1923309.800      399865.909     1923476.467      399881.534
     1923658.758      399911.048     1923706.328      399934.312
     1923716.760      399959.646     1923717.786      399982.229
     1923729.939      400006.534     1923757.717      400034.312
     1923795.911      400055.145     1923846.258      400067.298
     1923942.439      400072.506     1924008.336      400064.662
     1924150.078      400010.006     1924203.181      399979.983

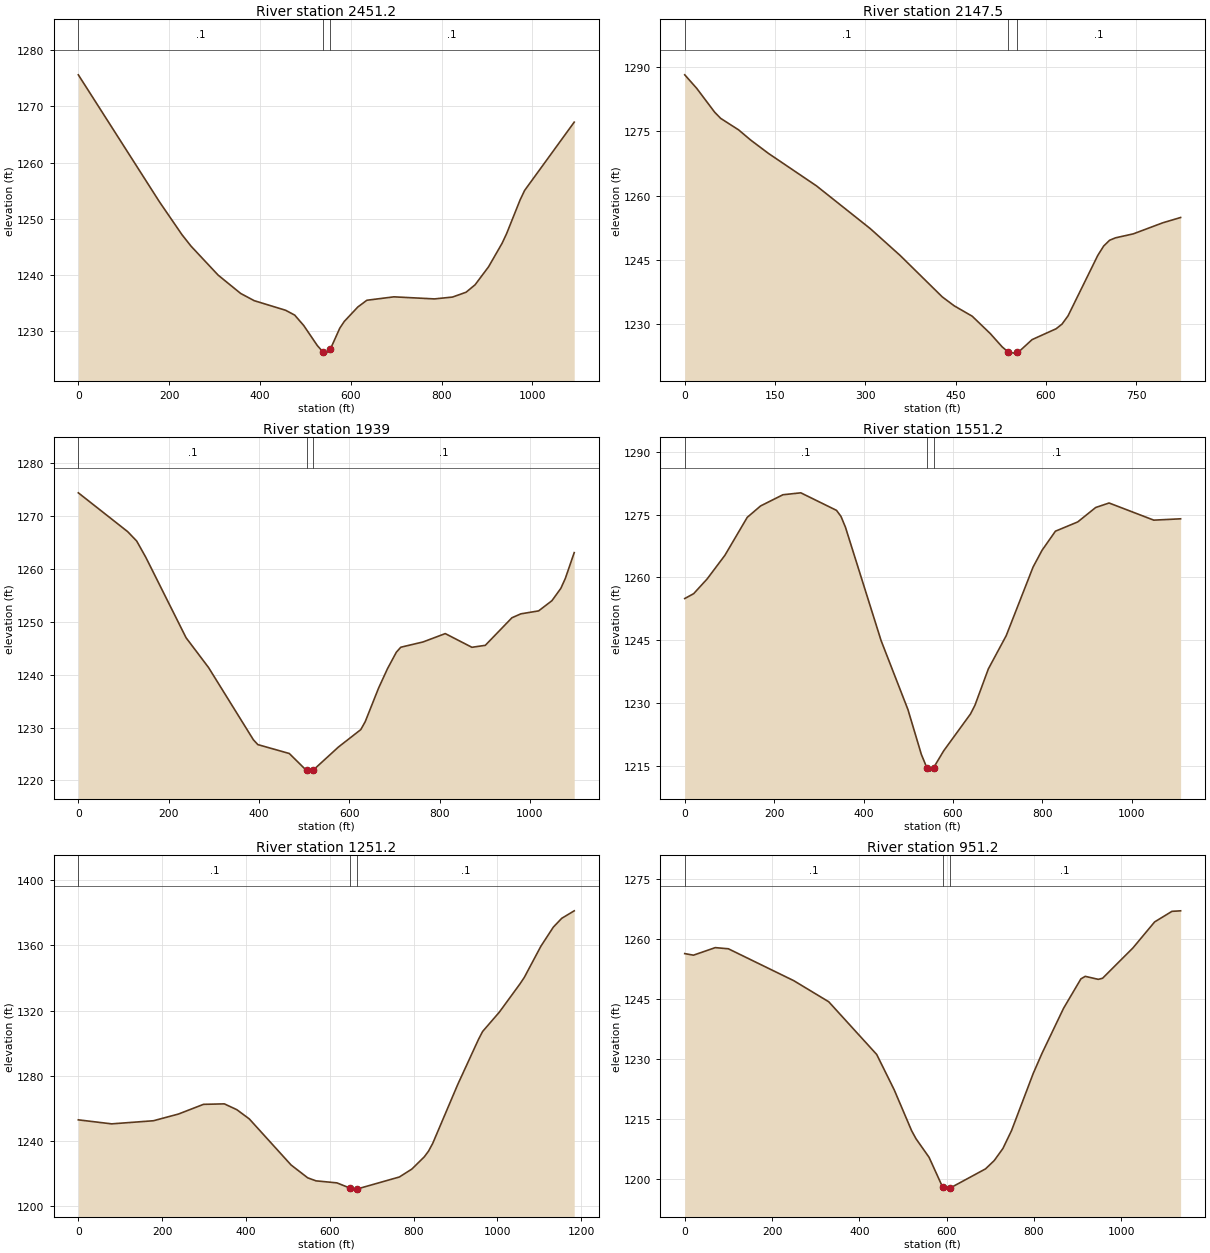
Type RM Length L Ch R = 1 ,2451.2,302.1,303.7,305.2
XS GIS Cut Line= 3
     1922237.753      401004.774     1922100.730      400476.247
     1921963.707      399947.720
#Sta/Elev= 30
       0 1275.64   178.7 1252.98   228.3 1247.12   248.2 1245.08   307.8 1239.92
   357.4 1236.65   387.2 1235.36   456.6 1233.64   476.5 1232.78   496.4 1230.92
   526.2 1227.36   538.5 1226.23   546.0 1226.00   553.5 1226.66   555.9 1226.87
   575.8 1230.46   585.7 1231.66   615.5 1234.23   635.4 1235.43   694.9 1236.04
   784.2 1235.67   824.0 1236.00   853.8 1236.86   873.6 1238.18   903.4 1241.40
   933.2 1245.60   943.1 1247.31   972.9 1253.34   982.8 1255.02  1092.0 1267.20
#Mann= 3 , 0 , 0
       0     0.1       0   538.5   0.045       0   553.5     0.1       0
Bank Sta=   538.5,   553.5
Exp/Cntr=0.3,0.1

Type RM Length L Ch R = 1 ,2147.5,221.3,208.5,195.8
XS GIS Cut Line= 3
     1922498.564      400959.208     1922378.197      400313.863
     1922331.203      400153.531
#Sta/Elev= 30
       0 1288.17    19.9 1285.02    49.7 1279.46    59.7 1278.02    89.5 1275.34
   109.4 1272.98   139.2 1269.84   218.8 1262.29   308.3 1252.31   358.1 1246.03
   427.7 1236.42   447.6 1234.33   477.4 1231.92   507.3 1227.89   527.2 1224.77
   536.7 1223.62   547.1 1223.31   551.7 1223.58   557.0 1223.90   576.9 1226.46
   616.7 1228.98   626.6 1230.07   636.6 1231.99   686.0 1246.08   695.8 1248.27
   705.6 1249.61   715.4 1250.18   744.9 1251.10   794.1 1253.69   823.6 1254.92
#Mann= 3 , 0 , 0
       0     0.1       0   536.7   0.045       0   551.7     0.1       0
Bank Sta=   536.7,   551.7
Exp/Cntr=0.3,0.1

Type RM Length L Ch R = 1 ,1939,386,387.7,386.4
XS GIS Cut Line= 3
     1922933.137      400716.683     1922561.164      400316.192
     1922211.175      399890.256
#Sta/Elev= 30
       0 1274.35   109.3 1267.01   129.2 1265.24   149.1 1262.21   238.5 1246.97
   288.2 1241.35   387.6 1227.68   397.5 1226.77   467.1 1225.09   505.2 1221.88
   516.8 1221.76   520.2 1221.97   576.1 1226.33   625.3 1229.60   635.2 1231.11
   664.7 1237.44   684.4 1241.10   704.1 1244.23   713.9 1245.17   763.2 1246.17
   812.4 1247.75   871.4 1245.16   901.0 1245.53   960.0 1250.74   979.7 1251.48
  1019.1 1252.04  1048.6 1253.97  1068.3 1256.30  1078.2 1258.17  1097.9 1263.05
#Mann= 3 , 0 , 0
       0     0.1       0   505.2   0.045       0   520.2     0.1       0
Bank Sta=   505.2,   520.2
Exp/Cntr=0.3,0.1

Type RM Length L Ch R = 1 ,1551.2,292.7,300,306.8
XS GIS Cut Line= 3
     1923227.313      400529.457     1922883.248      400101.563
     1922480.041      399713.028
#Sta/Elev= 30
       0 1254.96    20.0 1256.13    49.9 1259.62    89.8 1265.29   139.8 1274.37
   169.7 1277.10   219.6 1279.77   259.6 1280.23   339.4 1276.04   349.4 1274.60
   359.4 1272.02   439.2 1244.89   499.2 1228.42   529.1 1217.73   541.6 1214.47
   549.1 1213.71   556.6 1214.54   579.1 1218.56   639.1 1227.38   649.1 1229.47
   679.0 1238.14   719.0 1246.10   779.0 1262.48   799.0 1266.48   829.0 1271.06
   879.0 1273.28   919.0 1276.72   949.0 1277.80  1049.0 1273.70  1109.0 1274.02
#Mann= 3 , 0 , 0
       0     0.1       0   541.6   0.045       0   556.6     0.1       0
Bank Sta=   541.6,   556.6
Exp/Cntr=0.3,0.1

Type RM Length L Ch R = 1 ,1251.2,292.5,299.9,314.3
XS GIS Cut Line= 3
     1923287.688      400477.041     1923058.305      399861.464
     1922805.184      399399.888
#Sta/Elev= 30
       0 1252.97    79.6 1250.51   179.2 1252.42   238.9 1256.53   298.6 1262.48
   348.4 1262.78   378.2 1259.22   408.1 1253.52   507.6 1225.31   547.4 1217.40
   567.3 1215.54   617.1 1214.31   649.4 1210.99   656.9 1210.47   664.4 1210.49
   766.2 1217.92   796.0 1222.79   825.8 1230.33   835.7 1233.77   845.6 1238.46
   905.2 1274.53   954.9 1302.31   964.8 1307.18  1004.6 1319.02  1054.2 1336.47
  1064.2 1340.33  1103.9 1359.50  1133.7 1371.26  1153.6 1376.61  1183.4 1381.21
#Mann= 3 , 0 , 0
       0     0.1       0   649.4   0.045       0   664.4     0.1       0
Bank Sta=   649.4,   664.4
Exp/Cntr=0.3,0.1

Type RM Length L Ch R = 1 ,951.2,302.8,307.4,308.3
XS GIS Cut Line= 3
     1923369.136      400471.231     1923351.658      399871.490
     1923422.560      399339.725
#Sta/Elev= 30
       0 1256.39    20.0 1256.00    70.0 1257.89   100.0 1257.60   250.0 1249.61
   330.0 1244.34   440.0 1231.14   480.0 1222.32   520.0 1212.06   530.0 1210.06
   560.0 1205.40   590.0 1198.19   592.5 1198.00   600.0 1197.44   607.5 1197.67
   689.4 1202.51   709.3 1204.59   729.2 1207.61   749.0 1212.10   798.7 1226.40
   818.6 1231.38   868.2 1242.70   908.0 1250.07   917.9 1250.70   947.7 1249.95
   957.6 1250.22  1027.2 1257.81  1076.9 1264.32  1116.6 1266.97  1136.5 1267.10
#Mann= 3 , 0 , 0
       0     0.1       0   592.5   0.045       0   607.5     0.1       0
Bank Sta=   592.5,   607.5
Exp/Cntr=0.3,0.1

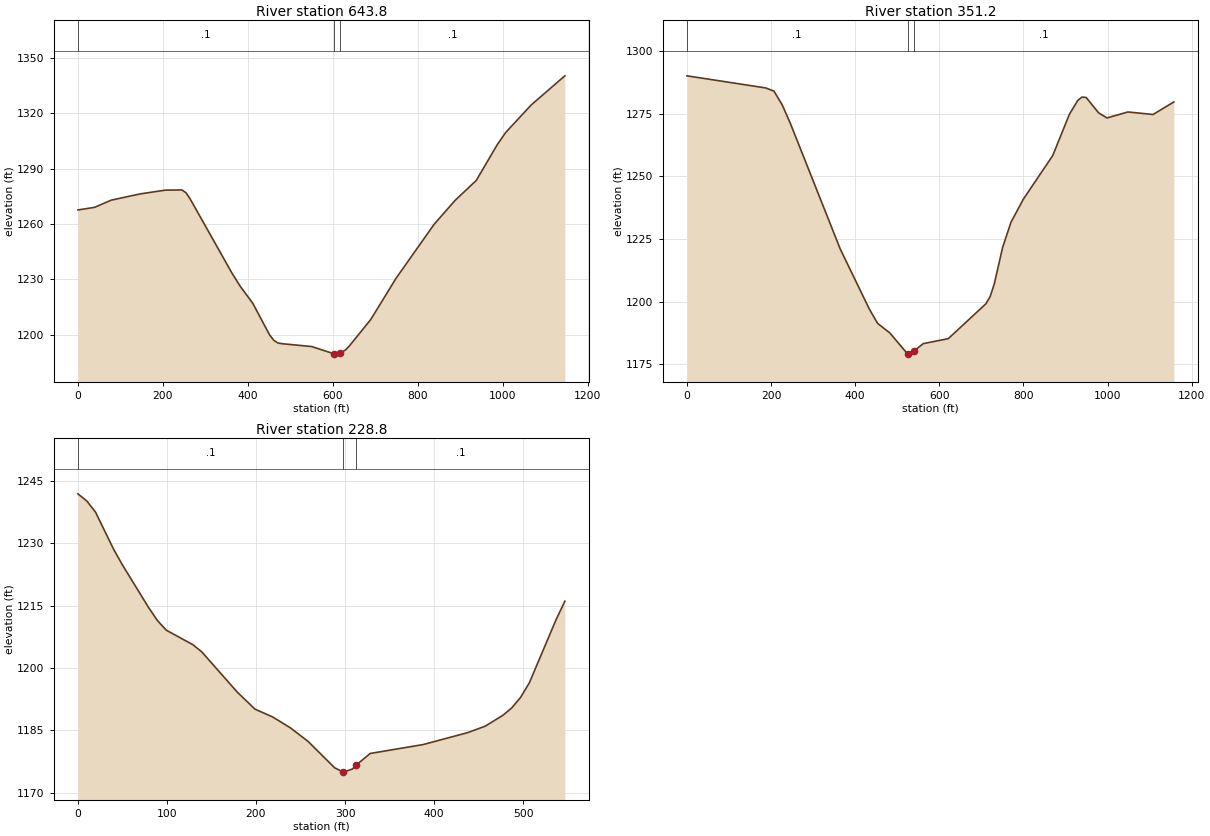
Type RM Length L Ch R = 1 ,643.8,294.8,292.6,292
XS GIS Cut Line= 3
     1923454.656      400483.018     1923625.605      400087.187
     1923747.610      399382.931
#Sta/Elev= 30
       0 1267.67    39.2 1269.10    78.4 1272.98   147.0 1276.40   205.8 1278.41
   245.0 1278.52   254.8 1276.92   264.6 1273.48   362.6 1233.44   382.2 1226.25
   411.6 1217.08   451.0 1200.01   461.0 1197.01   470.9 1195.58   480.8 1195.18
   550.3 1193.64   602.9 1189.71   609.8 1189.54   617.9 1190.06   629.7 1191.81
   639.6 1194.19   689.3 1208.34   748.8 1230.67   838.2 1259.87   887.8 1272.90
   937.4 1283.65   987.1 1303.15  1006.9 1309.71  1066.5 1324.53  1145.9 1340.37
#Mann= 3 , 0 , 0
       0     0.1       0   602.9   0.045       0   617.9     0.1       0
Bank Sta=   602.9,   617.9
Exp/Cntr=0.3,0.1

Type RM Length L Ch R = 1 ,351.2,128.8,122.3,114.5
XS GIS Cut Line= 3
     1923831.935      400599.605     1923870.753      400069.090
     1923957.152      399449.372
#Sta/Elev= 30
       0 1290.22   187.2 1285.38   206.9 1284.11   226.6 1278.58   246.3 1271.03
   364.5 1220.98   433.4 1197.06   453.1 1191.30   482.7 1187.38   524.4 1179.07
   531.9 1178.97   539.4 1180.18   561.7 1183.16   621.3 1185.16   710.7 1199.08
   720.6 1201.88   730.6 1207.01   750.4 1221.56   770.3 1231.68   800.1 1241.00
   869.6 1258.34   909.4 1274.90   929.2 1280.41   939.1 1281.72   949.1 1281.58
   978.9 1275.38   998.7 1273.39  1048.4 1275.77  1108.0 1274.76  1157.6 1279.78
#Mann= 3 , 0 , 0
       0     0.1       0   524.4   0.045       0   539.4     0.1       0
Bank Sta=   524.4,   539.4
Exp/Cntr=0.3,0.1

Type RM Length L Ch R = 1 ,228.8,235.6,228.7,221.8
XS GIS Cut Line= 2
     1924056.323      400365.003     1923942.294      399830.104
#Sta/Elev= 30
       0 1241.87     9.9 1240.18    19.9 1237.44    39.8 1228.68    49.7 1224.89
    79.6 1214.47    89.5 1211.36    99.4 1209.07   129.3 1205.58   139.2 1203.86
   179.0 1194.20   198.9 1190.10   218.8 1188.22   238.7 1185.60   258.5 1182.35
   288.4 1176.00   297.7 1175.02   298.3 1174.96   308.3 1175.71   312.7 1176.66
   328.2 1179.44   387.8 1181.59   437.5 1184.44   457.4 1186.00   477.3 1188.62
   487.2 1190.39   497.2 1192.93   507.1 1196.46   537.0 1211.59   546.9 1216.05
#Mann= 3 , 0 , 0
       0     0.1       0   297.7   0.045       0   312.7     0.1       0
Bank Sta=   297.7,   312.7
Exp/Cntr=0.3,0.1